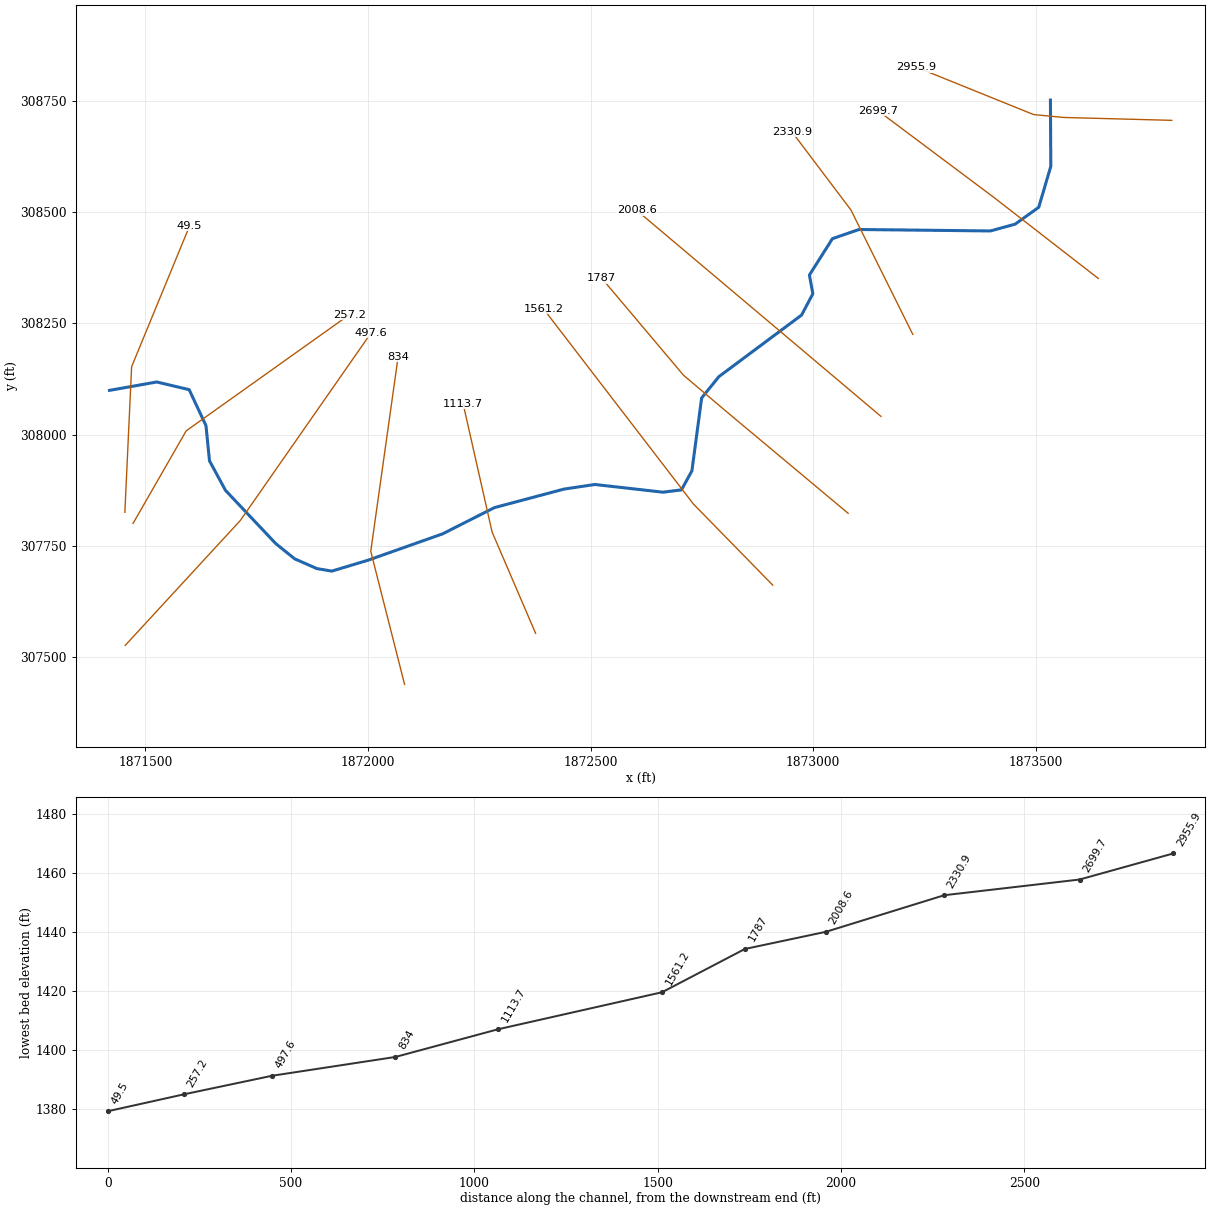
--- YORKRN.prj (project) ---

Proj Title=YORKRN
Current Plan=p01
Default Exp/Contr=0,0
English Units
Geom File=g01
Flow File=f01
Plan File=p01
BEGIN DESCRIPTION:
END DESCRIPTION:
DSS Export Rating Curves= 0
DSS Export Rating Curve Sorted= 0
DSS Export Volume Flow Curves= 0
DXF OffsetX= 0
DXF OffsetY= 0
DXF ScaleX= 0
DXF ScaleY= 0

--- YORKRN.p01 (plan) ---

Plan Title=Floodplain
Program Version=4.00
Geom File=g01
Flow File=f01
K Sum by GR=0
Std Step Tol=0.01
Critical Tol=0.01
Num of Std Step Trials=20
Max Error Tol=0.3
Flow Tol Ratio=0.001
Split Flow NTrial=30
Split Flow Tol=0.02
Split Flow Ratio=0.02
Log Output Level=0
Friction Slope Method=1
Unsteady Friction Slope Method=2
Unsteady Bridges Friction Slope Method=1
Global Log Level=0
CheckData=False
Run HTab=0
Run UNet=0
Run PostProcess=0
UNET Theta=0
UNET Theta Warmup=0
UNET ZTol=0
UNET ZSATol=0
UNET MxIter=0
UNET MaxInSteps=0
UNET DtIC=0
UNET DtMin=0
UNET MaxCRTS=0
UNET WFStab=0
UNET SFStab=0
UNET WFX=0
UNET SFX=0
UNET DSS MLevel=0
UNET DZMax Abort=0
UNET Convert EG Bridges=0
UNET Use Existing IB Tables=0
UNET Froude Limit=0
UNET Froude Power=0
Write IC File=0
Echo Input=False
Echo Output=False
Write Detailed=0

--- YORKRN.f01 (steady flow) ---

Flow Title=NFF Regression Equation
Program Version=4.00
Number of Profiles=1
Profile Names=P100yr
River Rch & RM=YORKRN,Main      ,2955.9
518.1194
River Rch & RM=YORKRN,Main      ,2330.9
543.2654
River Rch & RM=YORKRN,Main      ,257.2
586.2273
Boundary for River Rch & Prof#=YORKRN,Main      ,1
Up Type=0
Dn Type=3
Dn Slope=0.024192

--- YORKRN.g01 (geometry) ---

Geom Title=USGS 10m DEM
Program Version=4.00

River Reach=YORKRN     ,Main
Reach XY= 30
     1873532.987      308752.697     1873533.806      308603.654
     1873506.679      308511.423     1873453.511      308473.446
     1873398.172      308458.255     1873103.034      308461.510
     1873043.355      308440.894     1872991.655      308359.001
     1872999.399      308316.948     1872974.051      308268.920
     1872788.265      308130.276     1872749.588      308082.303
     1872727.696      307918.285     1872704.268      307875.468
     1872662.602      307870.259     1872509.824      307887.620
     1872440.379      307877.204     1872284.129      307835.537
     1872167.810      307776.509     1872001.143      307717.482
     1871918.896      307692.619     1871885.005      307698.406
     1871835.430      307720.343     1871793.069      307754.544
     1871680.100      307874.397     1871644.198      307940.829
     1871636.289      308020.042     1871598.547      308100.966
     1871525.847      308118.327     1871419.546      308099.426

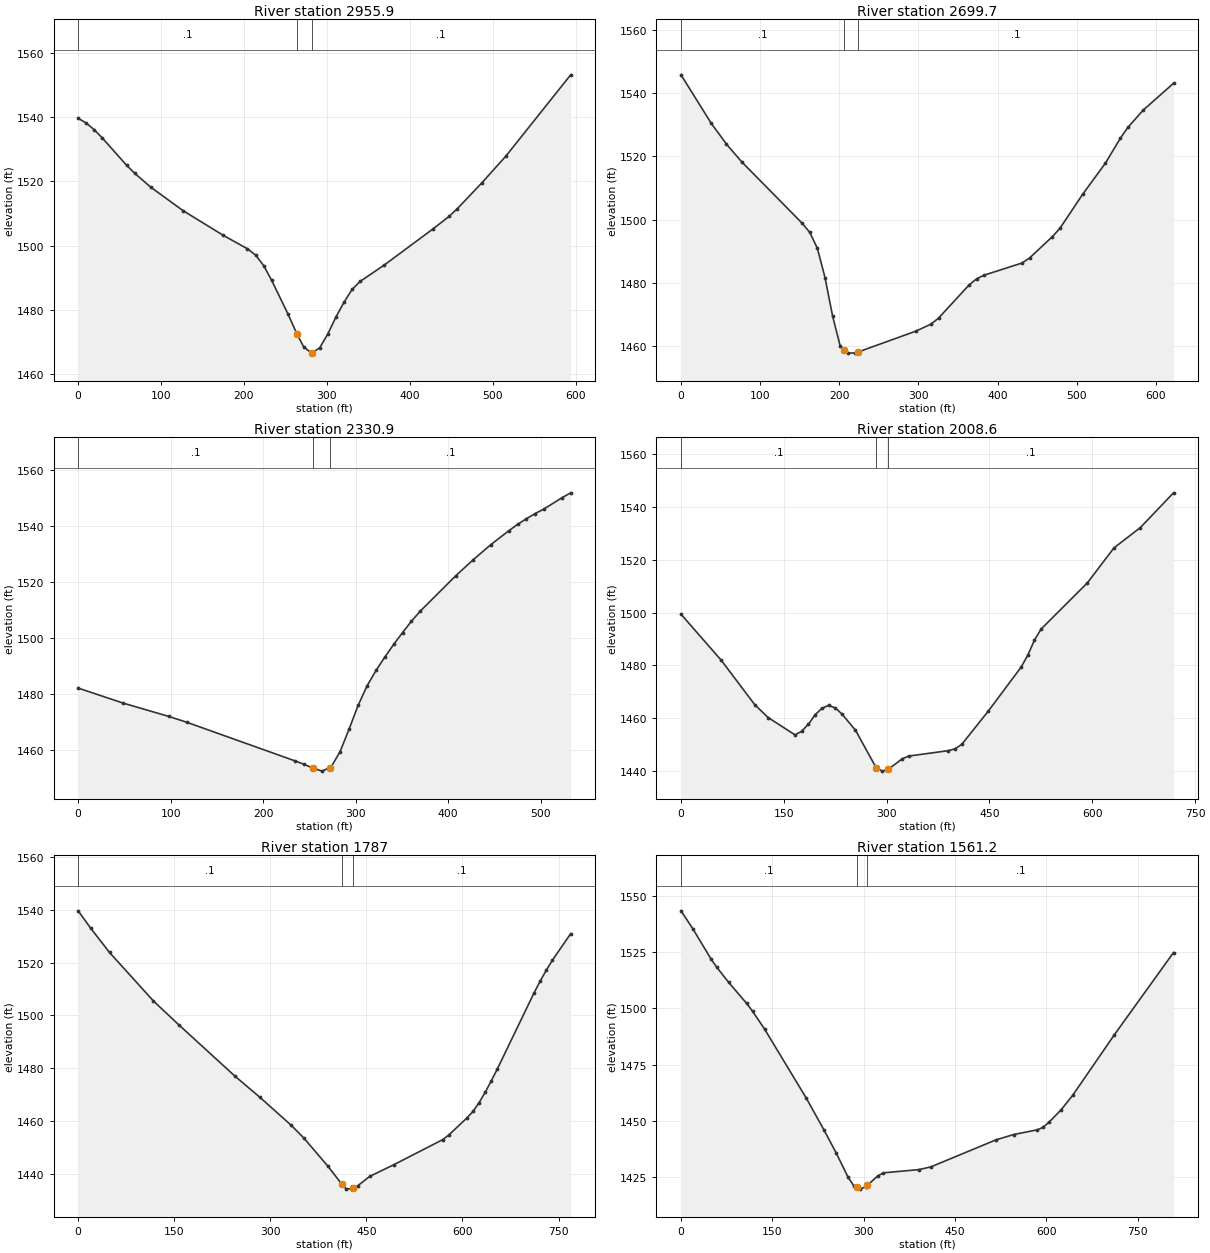
Type RM Length L Ch R = 1 ,2955.9,269.5,256.2,242.8
XS GIS Cut Line= 4
     1873805.445      308707.192     1873562.389      308713.702
     1873495.115      308720.213     1873232.528      308826.549
#Sta/Elev= 30
       0 1539.66     9.7 1538.15    19.4 1536.08    29.2 1533.49    58.4 1525.02
    68.1 1522.54    87.5 1518.21   126.4 1510.91   175.1 1503.19   204.2 1499.01
   214.0 1497.07   223.7 1493.79   233.4 1489.17   252.8 1478.84   263.7 1472.61
   272.1 1468.42   281.7 1466.54   291.4 1468.22   301.1 1472.51   310.7 1477.68
   320.5 1482.32   330.3 1486.35   340.0 1488.85   369.4 1494.00   428.0 1505.22
   447.5 1509.13   457.3 1511.50   486.6 1519.47   515.9 1527.89   594.0 1553.17
#Mann= 3 , 0 , 0
       0     0.1       0   263.7   0.045       0   281.7     0.1       0
Bank Sta=263.7,281.7
Exp/Cntr=0.3,0.1

Type RM Length L Ch R = 1 ,2699.7,379.1,368.8,358
XS GIS Cut Line= 3
     1873640.514      308351.289     1873406.139      308533.581
     1873145.723      308728.893
#Sta/Elev= 30
       0 1545.82    38.3 1530.44    57.5 1523.87    76.6 1518.30   153.2 1498.81
   162.8 1495.91   172.4 1490.87   182.0 1481.61   191.6 1469.42   201.1 1460.06
   206.2 1458.81   210.7 1457.70   220.3 1457.76   224.2 1458.09   296.9 1464.67
   316.1 1466.90   325.6 1468.82   363.9 1479.24   373.5 1481.22   383.1 1482.39
   431.0 1486.24   440.5 1487.83   469.3 1494.58   478.8 1497.19   507.6 1508.00
   536.3 1517.83   555.4 1525.82   565.0 1529.25   584.1 1534.64   622.4 1543.13
#Mann= 3 , 0 , 0
       0     0.1       0   206.2   0.045       0   224.2     0.1       0
Bank Sta=206.2,224.2
Exp/Cntr=0.3,0.1

Type RM Length L Ch R = 1 ,2330.9,313.5,322.3,331.6
XS GIS Cut Line= 3
     1873223.848      308225.421     1873084.959      308505.369
     1872952.580      308681.150
#Sta/Elev= 30
       0 1482.07    48.8 1476.69    97.7 1471.97   117.2 1469.89   234.4 1456.07
   244.2 1454.84   254.4 1453.42   263.7 1452.40   272.4 1453.67   273.4 1453.82
   283.2 1459.34   293.0 1467.44   302.7 1475.87   312.5 1482.92   322.1 1488.37
   331.6 1493.14   341.2 1497.68   350.8 1501.92   360.4 1505.96   369.9 1509.56
   408.2 1522.17   427.3 1527.96   446.4 1533.37   465.6 1538.27   475.2 1540.56
   484.7 1542.59   494.3 1544.44   503.9 1546.11   523.0 1550.05   532.6 1551.84
#Mann= 3 , 0 , 0
       0     0.1       0   254.4   0.045       0   272.4     0.1       0
Bank Sta=254.4,272.4
Exp/Cntr=0.3,0.1

Type RM Length L Ch R = 1 ,2008.6,221.3,221.6,221.2
XS GIS Cut Line= 3
     1873152.233      308040.959     1872928.037      308230.575
     1872603.529      308504.754
#Sta/Elev= 30
       0 1499.39    58.7 1481.98   107.7 1465.14   127.2 1460.29   166.4 1453.75
   176.2 1455.15   186.0 1457.84   195.8 1461.39   205.5 1463.77   215.3 1464.88
   225.1 1463.96   234.9 1461.61   254.5 1455.53   284.6 1441.38   293.6 1440.04
   302.6 1440.75   322.6 1444.68   332.2 1445.73   390.2 1447.79   399.8 1448.49
   409.5 1450.13   448.1 1462.67   496.4 1479.45   506.0 1483.95   515.7 1489.61
   525.4 1493.79   592.9 1511.26   631.6 1524.46   670.2 1532.17   718.5 1545.30
#Mann= 3 , 0 , 0
       0     0.1       0   284.6   0.045       0   302.6     0.1       0
Bank Sta=284.6,302.6
Exp/Cntr=0.3,0.1

Type RM Length L Ch R = 1 ,1787,231.2,225.8,220.1
XS GIS Cut Line= 4
     1873078.622      307822.766     1872800.844      308055.405
     1872708.830      308133.530     1872524.802      308352.280
#Sta/Elev= 30
       0 1539.61    19.6 1533.01    49.0 1523.83   117.5 1505.47   156.7 1496.53
   244.8 1476.99   284.0 1468.93   333.0 1458.31   352.5 1453.51   390.2 1442.80
   411.5 1436.12   418.0 1434.40   427.3 1434.21   429.5 1434.52   436.6 1435.50
   455.2 1439.04   492.6 1443.43   568.8 1452.92   578.3 1454.64   606.9 1461.16
   616.4 1463.64   626.0 1466.99   635.5 1470.92   645.0 1475.24   654.6 1479.83
   711.7 1508.52   721.2 1512.97   730.8 1517.11   740.3 1520.89   768.9 1530.95
#Mann= 3 , 0 , 0
       0     0.1       0   411.5   0.045       0   429.5     0.1       0
Bank Sta=411.5,429.5
Exp/Cntr=0.3,0.1

Type RM Length L Ch R = 1 ,1561.2,458.9,447.5,435.8
XS GIS Cut Line= 3
     1872909.177      307661.185     1872731.226      307843.476
     1872394.093      308283.232
#Sta/Elev= 30
       0 1543.47    19.6 1535.42    49.0 1522.18    58.8 1518.32    78.4 1511.60
   107.8 1502.27   117.6 1498.73   137.2 1490.86   205.8 1460.08   235.2 1445.74
   254.8 1435.74   274.2 1425.00   283.9 1421.04   288.3 1420.38   293.6 1419.58
   303.4 1420.66   306.3 1421.33   322.8 1425.40   332.5 1426.84   390.8 1428.27
   410.3 1429.48   517.2 1441.50   546.4 1443.89   585.3 1445.98   595.0 1447.15
   604.7 1449.44   624.2 1454.86   643.6 1461.45   711.6 1488.24   808.9 1524.90
#Mann= 3 , 0 , 0
       0     0.1       0   288.3   0.045       0   306.3     0.1       0
Bank Sta=288.3,306.3
Exp/Cntr=0.3,0.1

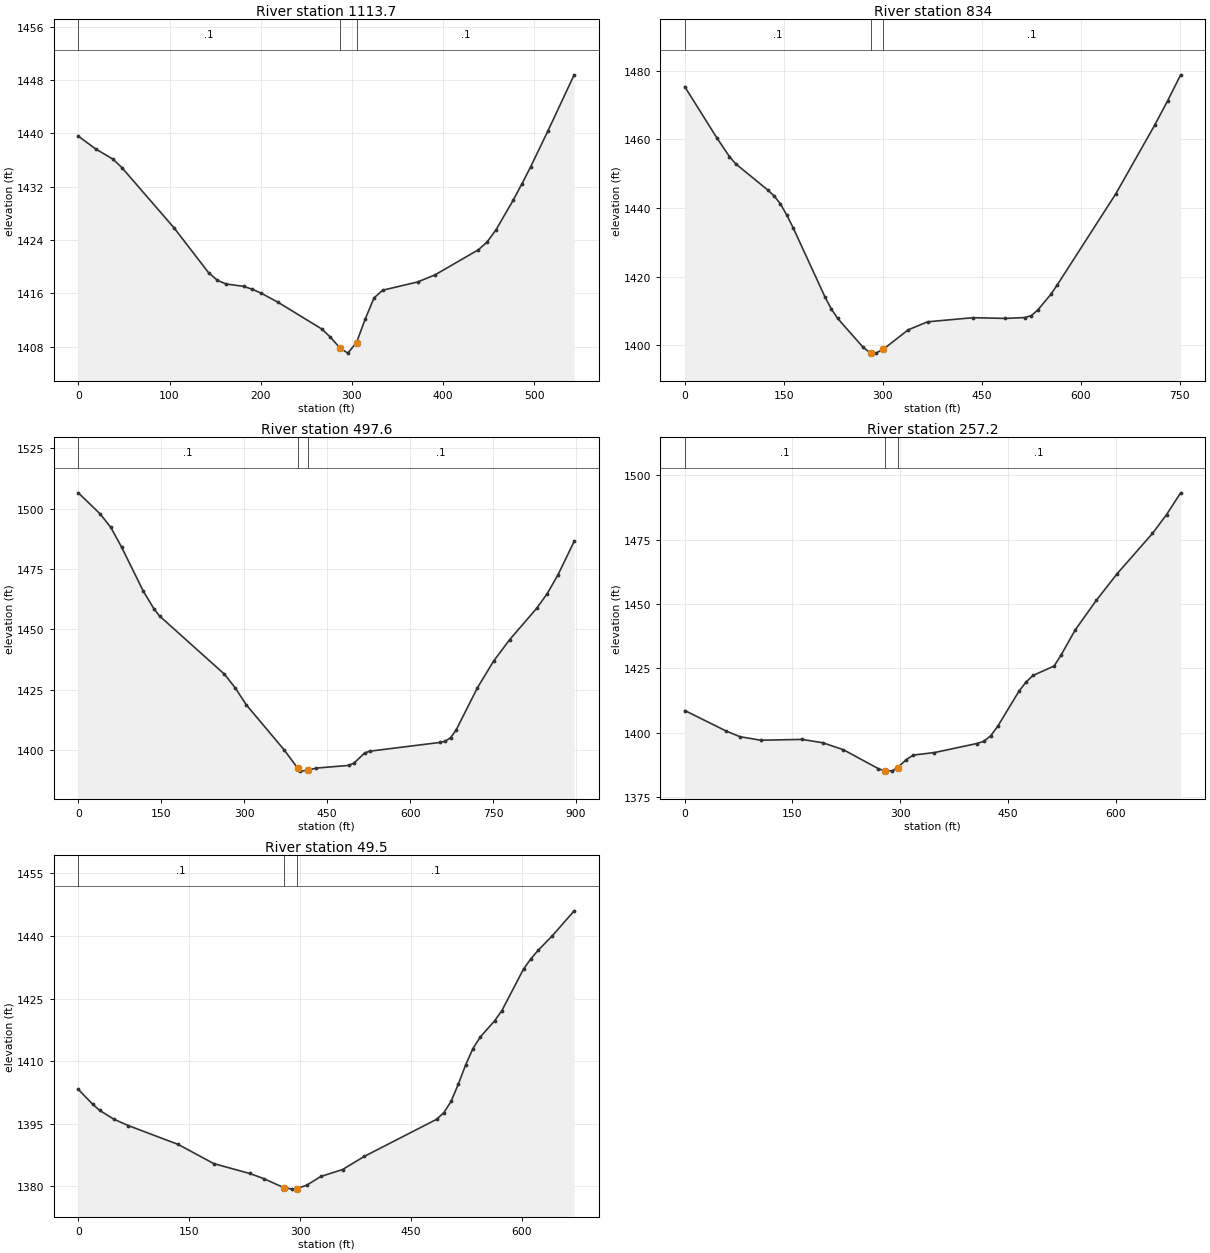
Type RM Length L Ch R = 1 ,1113.7,278.9,279.7,277.1
XS GIS Cut Line= 3
     1872376.625      307552.678     1872278.969      307780.542
     1872213.865      308069.171
#Sta/Elev= 30
       0 1439.60    19.1 1437.67    38.1 1436.14    47.7 1434.89   104.9 1425.86
   143.0 1419.09   152.6 1417.97   162.1 1417.42   181.2 1417.07   190.7 1416.63
   200.2 1416.07   219.3 1414.66   267.0 1410.67   276.5 1409.44   287.1 1407.81
   295.6 1407.05   305.1 1408.64   314.7 1412.18   324.3 1415.33   333.8 1416.49
   372.0 1417.72   391.1 1418.78   438.8 1422.56   448.3 1423.72   457.9 1425.51
   477.0 1430.01   486.5 1432.44   496.1 1435.01   515.2 1440.44   543.8 1448.80
#Mann= 3 , 0 , 0
       0     0.1       0   287.1   0.045       0   305.1     0.1       0
Bank Sta=287.1,305.1
Exp/Cntr=0.3,0.1

Type RM Length L Ch R = 1 ,834,357.2,336.4,318.8
XS GIS Cut Line= 3
     1872082.354      307437.660     1872006.400      307737.140
     1872067.928      308175.374
#Sta/Elev= 30
       0 1475.34    48.3 1460.52    67.6 1455.00    77.2 1452.86   125.5 1445.28
   135.2 1443.55   144.8 1441.24   154.5 1437.97   164.1 1434.29   212.4 1414.09
   222.1 1410.55   231.7 1407.80   270.3 1399.39   280.0 1397.94   282.9 1397.86
   289.6 1397.69   300.9 1398.82   338.5 1404.47   368.0 1406.82   436.8 1408.02
   486.0 1407.81   515.5 1408.06   525.3 1408.63   535.1 1410.29   554.8 1414.83
   564.6 1417.60   653.2 1444.12   712.2 1464.15   731.8 1471.24   751.5 1478.81
#Mann= 3 , 0 , 0
       0     0.1       0   282.9   0.045       0   300.9     0.1       0
Bank Sta=282.9,300.9
Exp/Cntr=0.3,0.1

Type RM Length L Ch R = 1 ,497.6,248.1,240.4,231.9
XS GIS Cut Line= 3
     1871454.996      307525.563     1871713.431      307806.584
     1872007.391      308229.163
#Sta/Elev= 30
       0 1506.56    39.2 1497.89    58.7 1492.27    78.3 1484.04   117.5 1465.84
   137.0 1458.45   146.8 1455.58   264.3 1431.45   283.9 1425.75   303.5 1418.86
   372.0 1400.18   396.7 1392.56   401.2 1391.33   414.7 1391.70   430.4 1392.59
   488.6 1393.70   498.3 1394.63   517.8 1398.86   527.5 1399.60   653.7 1403.21
   663.4 1403.70   673.2 1405.22   682.9 1408.24   721.7 1425.86   750.9 1436.88
   780.0 1445.78   828.6 1458.68   848.0 1464.85   867.4 1472.63   896.6 1486.46
#Mann= 3 , 0 , 0
       0     0.1       0   396.7   0.045       0   414.7     0.1       0
Bank Sta=396.7,414.7
Exp/Cntr=0.3,0.1

Type RM Length L Ch R = 1 ,257.2,186.1,207.7,230
XS GIS Cut Line= 3
     1871472.545      307800.074     1871591.903      308008.407
     1871958.768      308270.011
#Sta/Elev= 30
       0 1408.62    57.6 1400.64    76.8 1398.44   105.6 1397.07   163.3 1397.38
   192.1 1396.09   220.9 1393.38   269.5 1386.03   278.7 1385.11   279.3 1385.05
   289.1 1385.20   296.7 1386.46   308.7 1389.57   318.5 1391.30   347.8 1392.27
   406.6 1395.77   416.4 1396.62   426.2 1398.81   436.0 1402.53   465.4 1416.07
   475.2 1419.65   485.0 1422.24   514.4 1425.91   524.2 1430.20   543.8 1439.92
   573.1 1451.40   602.5 1461.89   651.5 1477.48   671.1 1484.80   690.7 1493.26
#Mann= 3 , 0 , 0
       0     0.1       0   278.7   0.045       0   296.7     0.1       0
Bank Sta=278.7,296.7
Exp/Cntr=0.3,0.1

Type RM Length L Ch R = 1 ,49.5,37.7,49.5,60.6
XS GIS Cut Line= 3
     1871454.099      307825.030     1871469.290      308152.721
     1871599.499      308469.561
#Sta/Elev= 30
       0 1403.23    19.3 1399.71    28.9 1398.20    48.2 1396.08    67.5 1394.57
   135.1 1390.04   183.3 1385.44   231.6 1383.09   250.9 1381.85   277.5 1379.71
   289.4 1379.33   295.5 1379.46   308.8 1380.27   328.0 1382.36   357.4 1384.03
   386.8 1387.18   484.6 1396.07   494.4 1397.68   504.2 1400.38   514.0 1404.54
   523.8 1409.08   533.6 1413.00   543.4 1415.75   562.9 1419.66   572.7 1422.08
   602.1 1432.08   611.9 1434.50   621.7 1436.54   641.2 1440.09   670.6 1446.04
#Mann= 3 , 0 , 0
       0     0.1       0   277.5   0.045       0   295.5     0.1       0
Bank Sta=277.5,295.5
Exp/Cntr=0.3,0.1